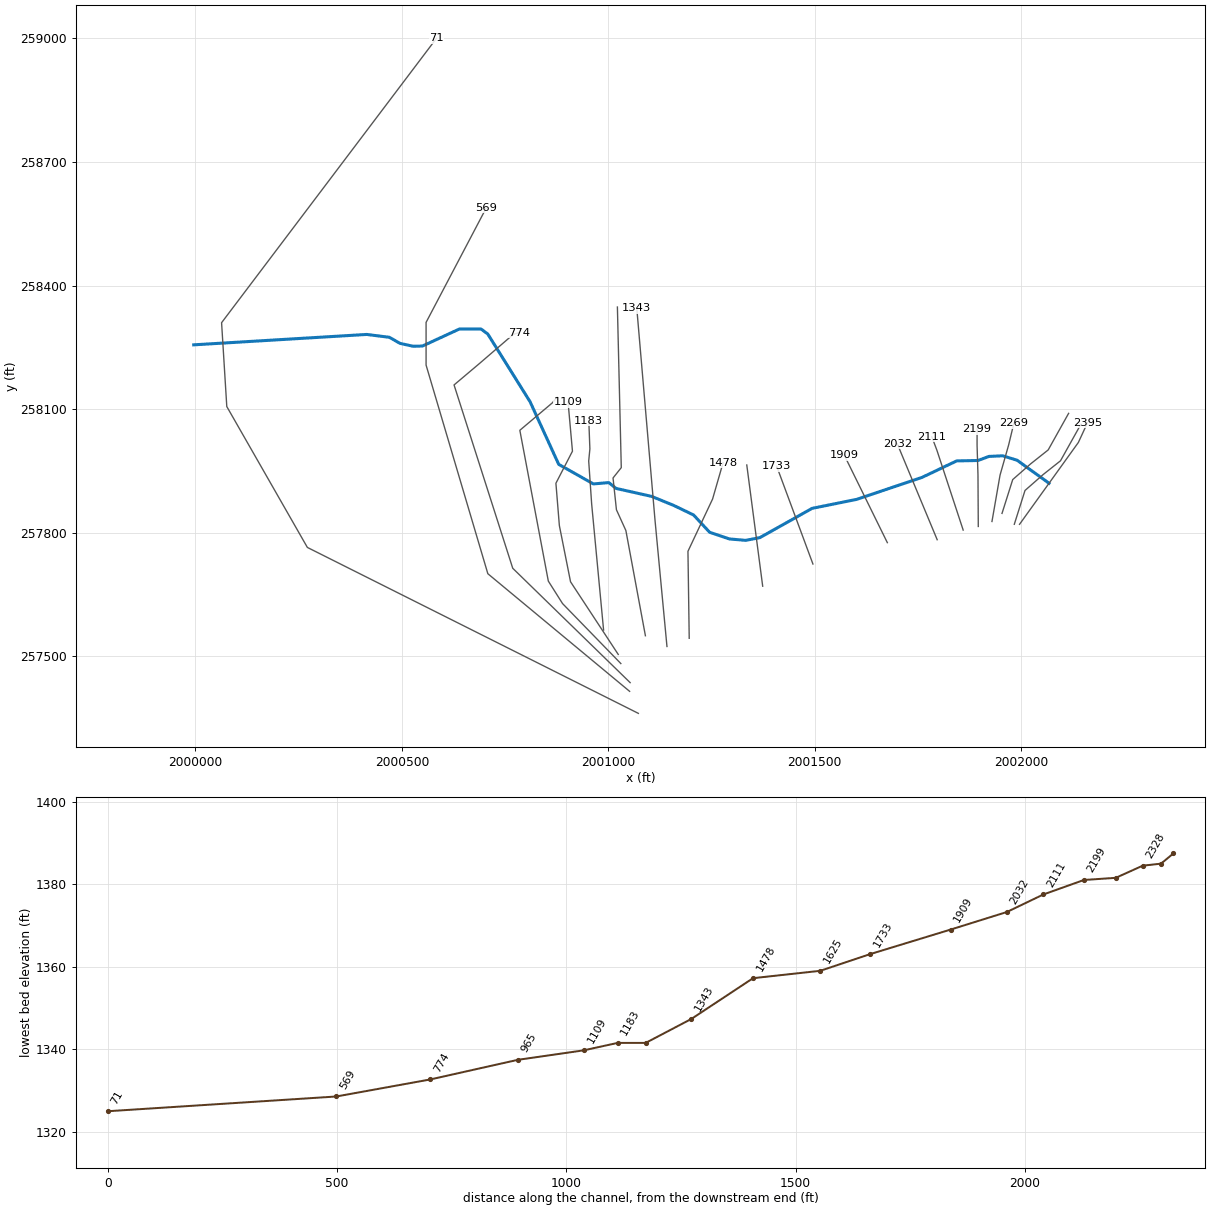
--- BRKSBR_AE.prj (project) ---

Proj Title=BRKSBR_AE
Current Plan=p01
Default Exp/Contr=0,0
English Units
Geom File=g01
Flow File=f01
Plan File=p01
BEGIN DESCRIPTION:
Stream Name: Brooks Branch
Flood Zone: Detailed
Summers County, West Virginia
HEC-RAS Version: 5.0.7
Hydrology Method: Regression
Model Notes:
END DESCRIPTION:
DSS Export Rating Curves= 0
DSS Export Rating Curve Sorted= 0
DSS Export Volume Flow Curves= 0
DXF OffsetX= 0
DXF OffsetY= 0
DXF ScaleX= 0
DXF ScaleY= 0

--- BRKSBR_AE.p01 (plan) ---

Plan Title=Floodplain
Program Version=5.07
Short Identifier=Floodplain
Geom File=g01
Flow File=f01
Subcritical Flow
K Sum by GR= 0
Std Step Tol= 0.01
Critical Tol= 0.01
Num of Std Step Trials= 20
Max Error Tol= 0.3
Flow Tol Ratio= 0.001
Split Flow NTrial= 30
Split Flow Tol= 0.02
Split Flow Ratio= 0.02
Log Output Level= 0
Friction Slope Method= 1
Unsteady Friction Slope Method= 2
Unsteady Bridges Friction Slope Method= 1
Parabolic Critical Depth
Global Vel Dist= 0 , 0 , 0
Global Log Level= 0
CheckData=True
Encroach Param=-1 ,5,5, 2
Encroach River=BRKSBR_AE
Encroach Reach=Main
Encroach Node=2395
       1   113.1  146.22
Encroach Node=2368
       1   104.5   146.4
Encroach Node=2328
       1   118.1   156.1
Encroach Node=2269
       1   146.3   172.7
Encroach Node=2199
       1   147.7  170.77
Encroach Node=2111
       1   150.6   176.3
Encroach Node=2032
       1   140.8   167.4
Encroach Node=1909
       1   111.6   139.8
Encroach Node=1733
       1   100.1   133.7
Encroach Node=1625
       1   104.5   132.3
Encroach Node=1478
       1     272   302.6
Encroach Node=1343
       1  339.75   381.1
Encroach Node=1244
       1   356.2     394
Encroach Node=1183
       1   346.2   374.2
Encroach Node=1109
       1   481.8   509.1
Encroach Node=965
       1  678.25  702.85
Encroach Node=774
       1   986.5  1015.5
Encroach Node=569
       1    1014    1049
Encroach Node=71
       1   649.3  1750.6
Mapping Interval=1HOUR
Computation Time Step Use Courant=        0
Computation Time Step Use Time Series=    0
Computation Time Step Count To Double=0
Computation Time Step Max Doubling=0
Computation Time Step Max Halving=0
Computation Time Step Residence Courant=0
Run HTab= 0
Run UNet= 0
Run Sediment= 0
Run PostProcess= 0
Run WQNet= 0
Run RASMapper= 0
UNET Theta= 0
UNET Theta Warmup= 0
UNET ZTol= 0
UNET ZSATol= 0
UNET MxIter= 0
UNET Max Iter WO Improvement= 0
UNET MaxInSteps= 0
UNET DtIC= 0
UNET DtMin= 0
UNET MaxCRTS= 0
UNET WFStab= 0
UNET SFStab= 0
UNET WFX= 1
UNET SFX= 1
UNET 1D Methodology=Finite Difference
UNET DSS MLevel= 1
UNET Pardiso=0
UNET DZMax Abort= 0
UNET Use Existing IB Tables= 0
UNET Froude Reduction=False
UNET Froude Limit= 0
UNET Froude Power= 0
UNET D1 Cores= 0
UNET D2 Coriolis=0
UNET D2 Cores= 0
UNET D2 Theta= 1
UNET D2 Theta Warmup= 1
UNET D2 Z Tol= 0.01
UNET D2 Volume Tol= 0.01
UNET D2 Max Iterations= 20
UNET D2 Equation= 0
UNET D2 RampUpFraction=0.1
UNET D2 TimeSlices= 1
UNET D2 BCVolumeCheck=0
UNET D1D2 MaxIter= 0
UNET D1D2 ZTol=0.01
UNET D1D2 QTol=0.1
UNET D1D2 MinQTol=1
Write IC File= 0
Write IC File at Fixed DateTime=0
Write IC File at Sim End=0
Echo Input=False
Echo Parameters=False
Echo Output=False
Write Detailed= 0
HDF Write Warmup=0
HDF Write Time Slices=0
HDF Flush=0
HDF Face Node Velocities=0
HDF Compression= 1
HDF Chunk Size= 1
HDF Spatial Parts= 1
HDF Use Max Rows=0
HDF Fixed Rows= 1
Calibration Method= 0
Calibration Iterations= 20
Calibration Max Change=0.05
Calibration Tolerance=0.2
Calibration Maximum=1.5
Calibration Minimum=0.5
Calibration Optimization Method= 1
WQ AD Non Conservative
WQ ULTIMATE=-1
WQ Max Comp Step=1HOUR
WQ Output Interval=15MIN
WQ Output Selected Increments= 0
WQ Output face flow=0
WQ Output face velocity=0
WQ Output face area=0
WQ Output face dispersion=0
WQ Output cell volume=0
WQ Output cell surface area=0
WQ Output cell continuity=0
WQ Output cumulative cell continuity=0
WQ Output face conc=0
WQ Output face dconc_dx=0
WQ Output face courant=0
WQ Output face peclet=0
WQ Output face adv mass=0
WQ Output face disp mass=0
WQ Output cell mass=0
WQ Output cell source sink temp=0
WQ Output nsm pathways=0
WQ Output nsm derived pathways=0
WQ Output MaxMinRange=-1
WQ Daily Max Min Mean=-1
WQ Daily Range=0
WQ Daily Time=0
WQ Create Restart=0
WQ Fixed Restart=0
WQ System Summary=0
WQ Write To DSS=0
WQ Use Fixed Temperature=0
Sorting and Armoring Iterations= 10
XS Update Threshold= 0.02
Bed Roughness Predictor= 0
Hydraulics Update Threshold= 0.02
Energy Slope Method= 1
Volume Change Method= 1
Sediment Retention Method= 0
XS Weighting Method= 0
Number of US Weighted Cross Sections= 1
Number of DS Weighted Cross Sections= 1
Upstream XS Weight=0
Main XS Weight=1
Downstream XS Weight=0
Number of DS XS's Weighted with US Boundary= 1
Upstream Boundary Weight= 1
Weight of XSs Associated with US Boundary= 0
Number of US XS's Weighted with DS Boundary= 1
Downstream Boundary Weight= 0.5
Weight of XSs Associated with DS Boundary= 0.5
Percentile Method= 0
Sediment Output Level= 3
Mass or Volume Output= 0
Output Increment Type= 1
Profile and TS Output Increment= 1
XS Output Flag= 0
XS Output Increment= 10
Write Gradation File= 0
Read Gradation Hotstart= 0
Write HDF5 File= 1
Write Binary Output= 1
Write DSS Sediment File= 0
SV Curve= 0
Specific Gage Flag= 0

--- BRKSBR_AE.f01 (steady flow) ---

Flow Title=Flows
Program Version=5.07
Number of Profiles= 7
Profile Names=01pct,FW,10pct,04pct,02pct,0_2pct,01plus
River Rch & RM=BRKSBR_AE,Main            ,2395
    1034    1034     559     735     880    1429    1529
Boundary for River Rch & Prof#=BRKSBR_AE,Main            , 1
Up Type= 0
Dn Type= 3
Dn Slope=0.02125
Boundary for River Rch & Prof#=BRKSBR_AE,Main            , 2
Up Type= 0
Dn Type= 3
Dn Slope=0.02125
Boundary for River Rch & Prof#=BRKSBR_AE,Main            , 3
Up Type= 0
Dn Type= 3
Dn Slope=0.02125
Boundary for River Rch & Prof#=BRKSBR_AE,Main            , 4
Up Type= 0
Dn Type= 3
Dn Slope=0.02125
Boundary for River Rch & Prof#=BRKSBR_AE,Main            , 5
Up Type= 0
Dn Type= 3
Dn Slope=0.02125
Boundary for River Rch & Prof#=BRKSBR_AE,Main            , 6
Up Type= 0
Dn Type= 3
Dn Slope=0.02125
DSS Import GetInterval= 0
DSS Import GetPeak= 0
DSS Import FillOption= 0

--- BRKSBR_AE.g01 (geometry) ---

Geom Title=Geometry
Program Version=5.07

River Reach=BRKSBR_AE       ,Main
Reach XY= 30
2002067.20050332257920.108045883     2001989.773      257976.013
     2001954.681      257986.774     2001921.608      257985.212
     2001895.046      257975.316      2001843.56      257974.366
     2001759.889      257934.431     2001600.953      257880.855
     2001493.483       257859.17     2001366.879      257788.088
     2001332.746      257781.454     2001292.963      257784.951
     2001245.306      257801.097     2001206.504      257843.024
     2001158.783       257866.09     2001104.829      257888.243
      2001018.75      257907.527     2001001.296       257921.67
     2000963.766       257918.47      2000879.81      257966.043
     2000810.584      258117.8072000708.16195426258282.299522868
 2000691.7128119258294.5361517662000639.40034858258294.574081582
 2000549.9389419258253.2164647722000527.28119778258252.671034611
2000495.24748826258259.789918418     2000469.785      258274.404
     2000414.924      258281.349     1999995.972      258256.109

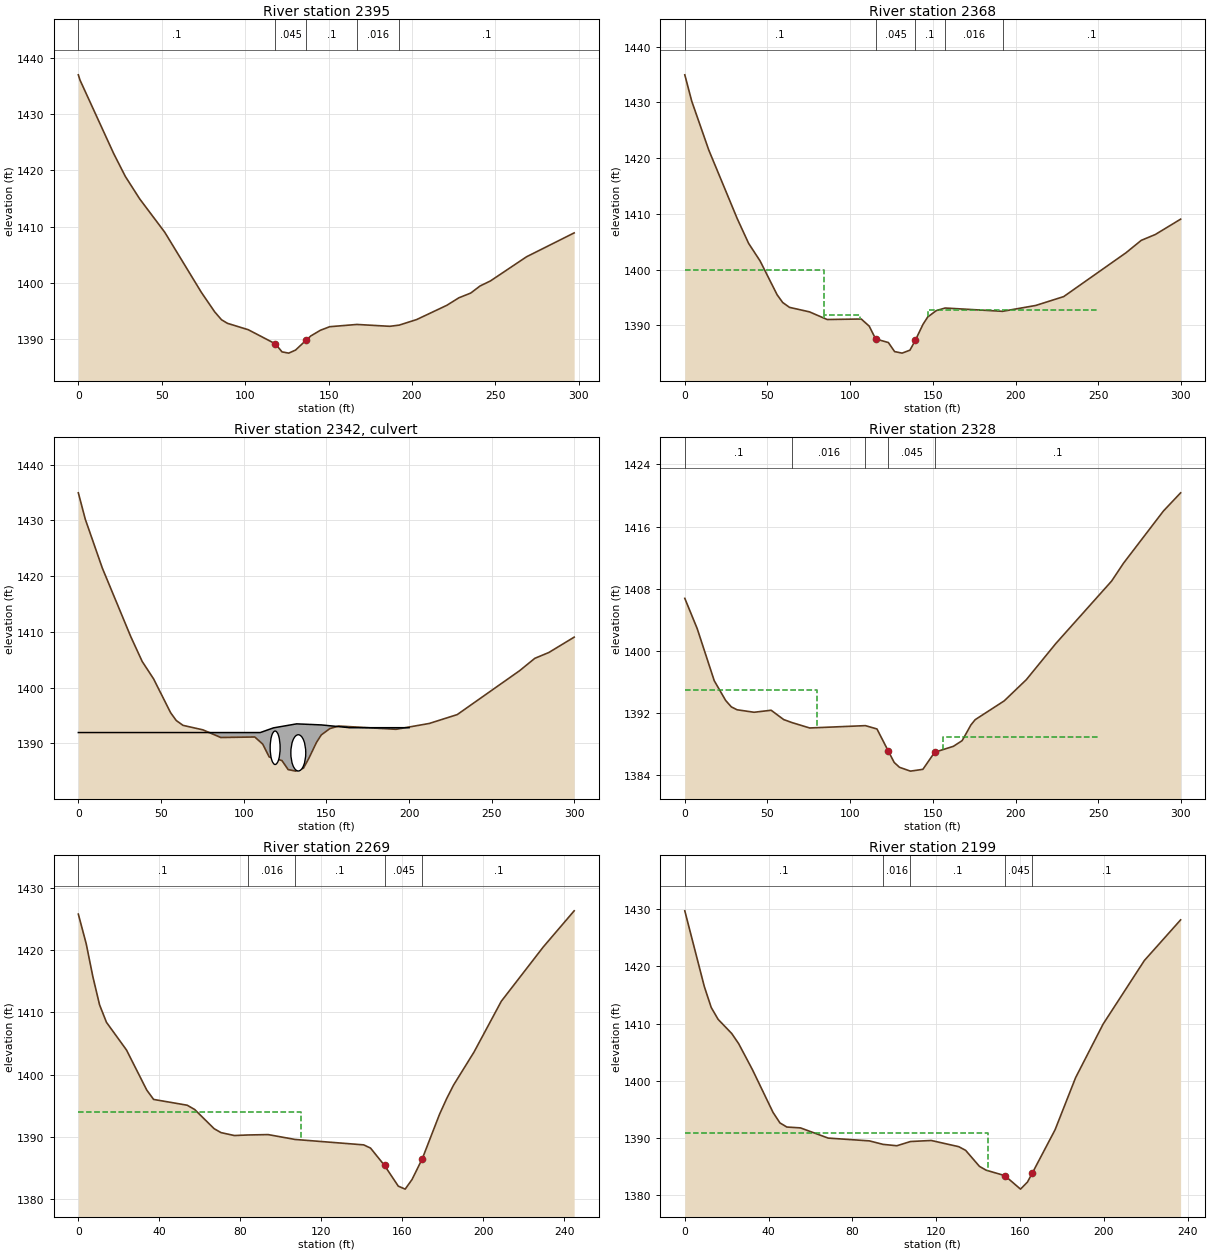
Type RM Length L Ch R = 1 ,2395    ,36.1,27.1,15.1
XS GIS Cut Line= 4
2001995.75198199257820.4197445882002017.18539399257850.362449737
 2002138.2625121258019.2337192282002160.32793774258067.005289432
#Sta/Elev= 30
       0 1436.93       1    1436    21.2 1422.95    28.2 1418.88    36.8  1414.9
    51.8 1408.99    73.7 1398.34    81.7 1394.87    85.8 1393.46    89.4 1392.82
   101.9 1391.68   118.1 1389.18   122.1 1387.75   126.1 1387.53   130.2 1388.07
   136.4 1389.79   139.4 1390.59   145.1 1391.59   150.7 1392.22     167 1392.62
   186.7 1392.29   192.3  1392.5   202.8 1393.49   220.9 1396.02   228.1 1397.35
   235.2 1398.19   240.8 1399.45     247 1400.34   268.7 1404.64   297.2 1408.87
#Mann= 5 ,-1 , 0
       0      .1       0   118.1    .045       0   136.4      .1       0
     167    .016       0   192.3      .1       0
Bank Sta=118.1,136.4
XS Rating Curve= 0 ,0
Exp/Cntr(USF)=0,0
Exp/Cntr=0.5,0.3

Type RM Length L Ch R = 1 ,2368    ,40.5,39.9,43.8
BEGIN DESCRIPTION:
Channel burned based on survey: 54089BRB042CU
END DESCRIPTION:
XS GIS Cut Line= 5
2001983.07408371257820.5293351582002008.99376604257902.608329177
2002052.67323069257941.0078585432002094.91271299257974.607446738
2002144.35210705258063.406358397
#Sta/Elev= 30
       0 1434.96     4.2 1430.23    14.5 1421.47    31.7 1409.17    38.6 1404.72
    45.5 1401.59    55.8 1395.52    59.2 1394.12    63.3 1393.25    75.4 1392.44
    86.1 1391.07   106.7 1391.16   111.5 1389.88   115.4 1387.58   123.1 1386.94
  126.84 1385.32  131.38 1385.04  136.13 1385.57   139.4 1387.34     144 1390.19
   146.9 1391.53   152.1 1392.67   157.4 1393.13   192.1 1392.54   212.2 1393.59
   229.1 1395.18   266.8 1403.05     276 1405.27   284.5 1406.32   299.8 1409.07
#Mann= 5 ,-1 , 0
       0      .1       0   115.4    .045       0   139.4      .1       0
   157.4    .016       0   192.1      .1       0
#XS Ineff= 3 ,-1
       0      84    1400      84     106 1391.96     147     250 1392.83
Permanent Ineff=
       F       F       F
Bank Sta=115.4,139.4
XS Rating Curve= 0 ,0
Exp/Cntr(USF)=0,0
Exp/Cntr=0.5,0.3

Type RM Length L Ch R = 2 ,2342    ,,,
BEGIN DESCRIPTION:
Brooks Bridge
Survey Bridge Number: 54089BRB040
END DESCRIPTION:
Bridge Culvert--1,0,-1,-1, 0
Deck Dist Width WeirC Skew NumUp NumDn MinLoCord MaxHiCord MaxSubmerge Is_Ogee
10,12,2.6,0, 7, 7, , , 0.98, 0, 0,0,,
       0     110     118     132     147     164     200
 1391.96 1391.96  1392.81393.5191393.328 1392.83 1392.83
                                                        
       0     110     118     132     147     164     200
 1391.96 1391.96  1392.81393.5191393.328 1392.83 1392.83
                                                        
BR Coef=-1 , 1 , 0 ,, 0 ,,,0.8,0,1.2,0,
WSPro=,,,, 1 ,,,, 0 ,,,, 0 ,,,,-1 ,-1 ,-1 , 0 , 0 , 0 , 0 , 0
Culvert=1,6,,31,0.019,0.9,1,2,3,1386.232,119,1385.418,127,Culvert #1  , 0 ,7
     119     127
BC Culvert Barrel=1,Barrel1,0
Culvert Bottom n=0.019
Culvert=4,6.5,9,20,0.019,0.5,1,29,1,1385.066,133,1384.572,135,Culvert #2  , 0 ,7
     133     135
BC Culvert Barrel=1,Barrel1,0
Culvert Bottom n=0.019
BC Design=,, 0 ,, 0 ,,,,,,
BC Use User HTab Curves=0
BC User HTab FreeFlow(D)= 0

Type RM Length L Ch R = 1 ,2328    ,38.8,58.8,76.7
BEGIN DESCRIPTION:
Channel burn based on survey: 54089BRB038CD
END DESCRIPTION:
XS GIS Cut Line= 5
2001953.31444846257846.9290115972001979.23413078257929.008005616
2002022.91359543257967.4075349822002065.15307773258001.007123177
2002114.59247179258089.806034836
#Sta/Elev= 30
       0 1406.77     7.5 1402.88    17.8 1396.18    24.7 1393.64    28.1 1392.82
    31.6 1392.44    41.9 1392.12    52.2 1392.38    59.8 1391.18      65 1390.78
    75.5  1390.1   109.2  1390.4   116.2 1389.97   123.1 1387.11   126.6 1385.67
  129.82 1385.04  136.44 1384.55  143.96 1384.78   151.1 1386.98   162.4 1387.74
   167.7 1388.47     173 1390.49   175.6 1391.17   193.1 1393.58   206.5 1396.31
   224.3 1400.95   258.1    1409   265.3  1411.3   289.4    1418   299.8 1420.34
#Mann= 5 ,-1 , 0
       0      .1       0      65    .016       0   109.2      .1       0
   123.1    .045       0   151.1      .1       0
#XS Ineff= 3 ,-1
       0      80    1395      80   118.1  1388.5   156.1     250    1389
Permanent Ineff=
       F       F       F
Bank Sta=123.1,151.1
XS Rating Curve= 0 ,0
Exp/Cntr(USF)=0,0
Exp/Cntr=0.5,0.3

Type RM Length L Ch R = 1 ,2269    ,61.7,69.4,72.9
XS GIS Cut Line= 4
2001928.99215755257827.2859318752001948.54747343257939.877144522
2001969.28795997258012.7651400782001982.10894391258066.156169844
#Sta/Elev= 30
       0 1425.78     3.9 1421.01     7.2  1415.7    10.5  1411.2    13.9  1408.4
    23.8 1403.95    33.8 1397.52    37.2 1396.01    53.8 1395.08    57.5 1394.39
    67.1 1391.31    70.5 1390.68    77.1 1390.21    83.8  1390.3    93.8 1390.36
   107.1 1389.58     141 1388.71   144.4 1388.19   151.3  1385.4   158.1 1382.08
   161.5  1381.6   164.9 1383.15     170 1386.52   178.5 1393.64     182 1396.14
   185.4 1398.31   195.5 1403.61     209 1411.78   229.7 1420.49     245 1426.31
#Mann= 5 ,-1 , 0
       0      .1       0    83.8    .016       0   107.1      .1       0
   151.3    .045       0     170      .1       0
#XS Ineff= 2 , 0
             110    1394
Permanent Ineff=
       F       F
Bank Sta=151.3,170
XS Rating Curve= 0 ,0
Exp/Cntr(USF)=0,0
Exp/Cntr=0.3,0.1

Type RM Length L Ch R = 1 ,2199    ,84.3,88.3,91.6
XS GIS Cut Line= 4
2001895.85152219257815.2177953192001895.11993536257940.319142704
2001892.92517488258012.0146517322001892.95060279258051.795094764
#Sta/Elev= 30
       0 1429.71     9.3  1416.5    12.6 1412.83    15.9 1410.75    22.4 1408.27
    25.7  1406.5    32.3 1401.94    42.1 1394.49    45.4 1392.65    48.7 1391.93
    55.2 1391.78    68.4    1390    88.1 1389.51    94.6  1388.9   101.2 1388.66
   107.7  1389.4   117.6 1389.58   130.7  1388.5     134 1387.86   140.6 1385.06
   143.8 1384.39   152.7 1383.44   160.2 1381.08   163.5 1382.31  165.771383.846
   176.7 1391.46   186.5 1400.57   199.6 1409.91   219.3 1421.03   236.6 1428.13
#Mann= 5 ,-1 , 0
       0      .1       0    94.6    .016       0   107.7      .1       0
   152.7    .045       0  165.77      .1       0
#XS Ineff= 2 , 0
          144.45 1390.95
Permanent Ineff=
       F       F
Bank Sta=152.7,165.77
XS Rating Curve= 0 ,0
Exp/Cntr(USF)=0,0
Exp/Cntr=0.3,0.1

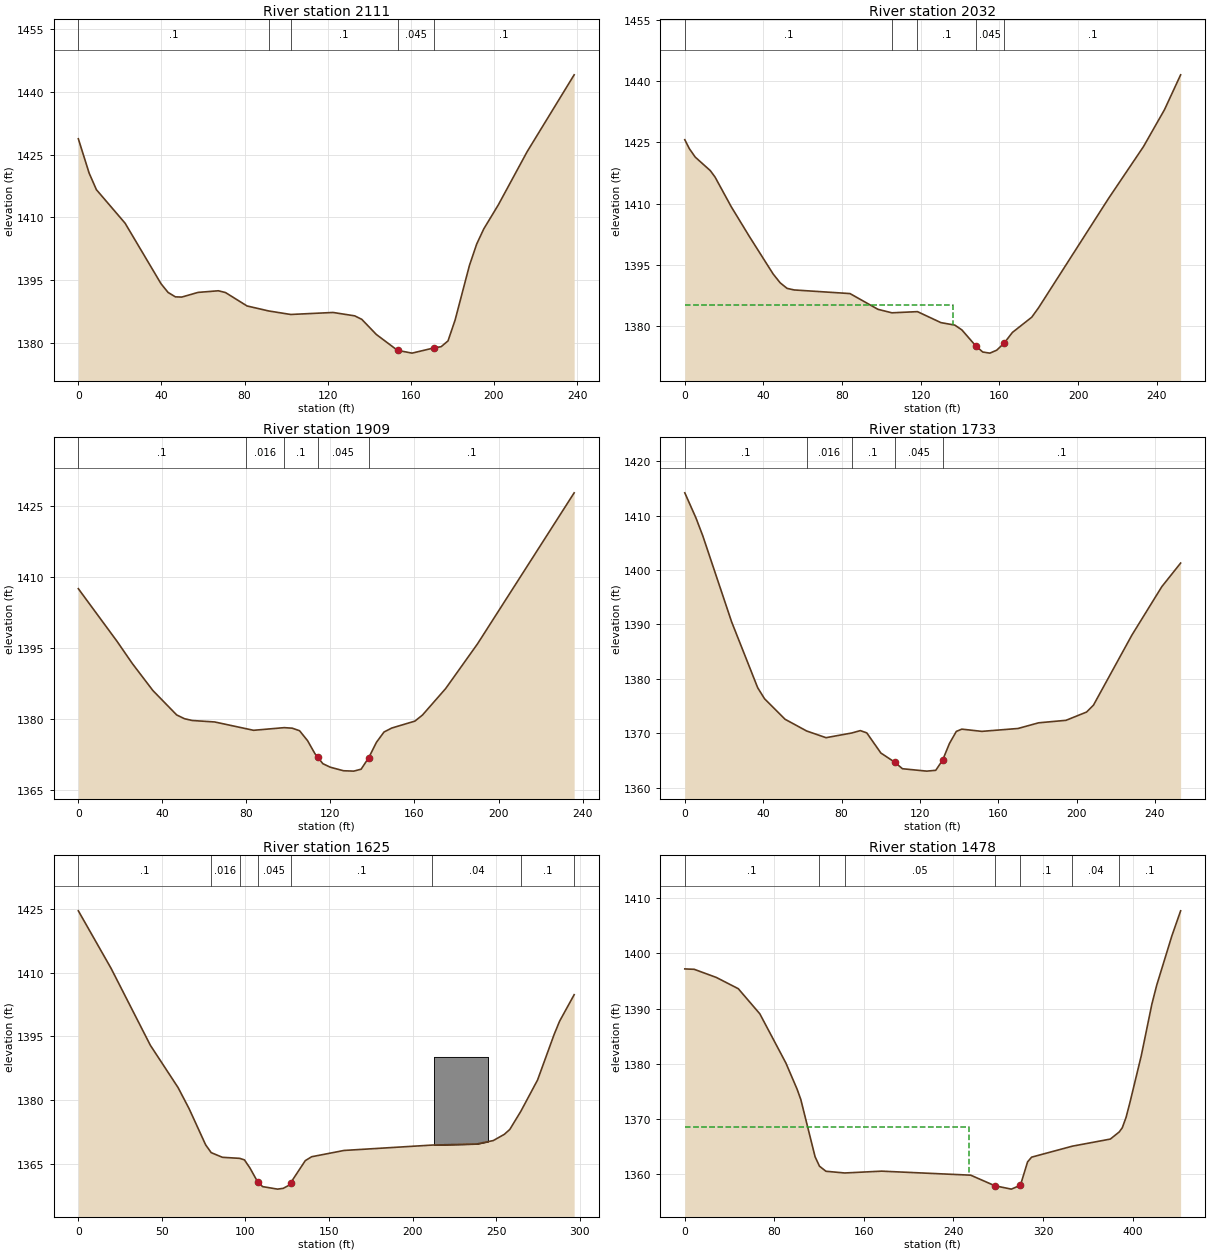
Type RM Length L Ch R = 1 ,2111    ,78.5,79.6,80.6
XS GIS Cut Line= 3
2001859.27218085257806.4387533972001795.62412692258000.309262503
 2001783.4474053258032.646994657
#Sta/Elev= 30
       0 1428.76     5.2 1420.56     8.7  1416.6    22.5  1408.6    39.8 1394.14
    43.2 1392.06    46.7 1391.01    49.8 1390.96    57.6 1392.07    67.4 1392.46
    70.8 1392.04    81.2 1388.83    91.6 1387.64   102.2  1386.8   122.6 1387.28
     133 1386.47   136.4 1385.64   143.4 1382.03   153.6 1378.23   160.6 1377.57
     171  1378.8   174.6 1379.11   177.9 1380.49   181.3 1385.46   188.2  1398.5
   191.7 1403.62   195.1 1407.23   202.1 1412.97     216  1425.7   238.6 1444.03
#Mann= 5 ,-1 , 0
       0      .1       0    91.6    .016       0   102.2      .1       0
   153.6    .045       0     171      .1       0
Bank Sta=153.6,171
XS Rating Curve= 0 ,0
Exp/Cntr(USF)=0,0
Exp/Cntr=0.3,0.1

Type RM Length L Ch R = 1 ,2032    ,121.8,122.5,124
XS GIS Cut Line= 2
2001796.35571374257783.0279749392001699.67446733258015.892407063
#Sta/Elev= 30
       0 1425.67     2.3 1423.48     5.3 1421.41      13 1418.07    15.4 1416.49
    23.6 1409.24    32.9 1401.88    44.9 1392.74    48.5 1390.56      52  1389.2
    55.6 1388.81      84 1387.92    98.2 1384.06   105.3  1383.2   118.3 1383.49
   130.2  1380.8   137.3 1380.18   140.9    1379     148 1375.05   151.5 1373.58
   155.1 1373.31   158.6 1374.03   162.41375.782   166.6  1378.4   176.4 1382.12
   179.9 1384.46   215.4 1411.22   233.2 1423.97   243.9 1433.04   252.1 1441.59
#Mann= 5 ,-1 , 0
       0      .1       0   105.3    .016       0   118.3      .1       0
     148    .045       0   162.4      .1       0
#XS Ineff= 2 , 0
           136.5    1385
Permanent Ineff=
       F       F
Bank Sta=148,162.4
XS Rating Curve= 0 ,0
Exp/Cntr(USF)=0,0
Exp/Cntr=0.3,0.1

Type RM Length L Ch R = 1 ,1909    ,177.6,176.1,174.4
XS GIS Cut Line= 2
2001675.62899533 257775.913848462001571.62154787257987.768635031
#Sta/Elev= 30
       0 1407.57    18.4 1396.47    25.7 1391.77    35.5 1386.06    46.8 1380.92
    50.5 1380.12    54.2 1379.74    64.9 1379.43    79.6 1378.03    83.4 1377.67
      98 1378.23   101.8 1378.12   105.3 1377.58   109.1 1375.49   112.6 1372.75
     114 1371.94   116.4 1370.62   119.9 1369.88   126.2 1369.13   131.1 1369.05
   134.6 1369.46   138.2 1371.87   141.9 1375.14   145.5 1377.31   149.2 1378.15
   160.2 1379.61   163.8 1380.89   174.8 1386.46     190 1395.92     236 1427.81
#Mann= 5 ,-1 , 0
       0      .1       0    79.6    .016       0      98      .1       0
     114    .045       0   138.2      .1       0
Bank Sta=114,138.2
XS Rating Curve= 0 ,0
Exp/Cntr(USF)=0,0
Exp/Cntr=0.3,0.1

Type RM Length L Ch R = 1 ,1733    ,110.1,108.4,104.7
XS GIS Cut Line= 2
2001495.45069224 257724.05441067 2001407.6659407257961.439997384
#Sta/Elev= 30
       0 1414.17     5.7 1409.56     9.2 1406.26    23.9 1390.48    37.2 1378.39
    40.7 1376.36    51.2 1372.59    62.2 1370.44    72.1 1369.21    85.2 1370.07
    89.6 1370.51    92.9 1370.09   100.1 1366.39   107.1 1364.73   111.1 1363.51
   123.5 1363.07   128.1 1363.22   131.6 1365.08   135.1 1368.15   138.6 1370.36
   141.4 1370.78   151.6 1370.37   170.1  1370.9   180.6 1371.94   194.6  1372.4
   205.1 1373.92   208.6 1375.18   228.2 1388.03   243.5 1396.94   253.1 1401.27
#Mann= 5 ,-1 , 0
       0      .1       0    62.2    .016       0    85.2      .1       0
   107.1    .045       0   131.6      .1       0
Bank Sta=107.1,131.6
XS Rating Curve= 0 ,0
Exp/Cntr(USF)=0,0
Exp/Cntr=0.3,0.1

Type RM Length L Ch R = 1 ,1625    ,153.8,146.6,138.6
XS GIS Cut Line= 2
2001373.78047281257670.2003791192001335.26218717257964.431888026
#Sta/Elev= 30
       0 1424.52    19.6 1410.98    43.1 1392.88    59.7 1382.92    66.3 1377.95
    76.2 1369.44    79.5 1367.62    86.2 1366.52    96.6 1366.27    99.4 1365.91
   102.7    1364   107.4 1360.67   110.3 1359.62   119.2 1359.03   122.6 1359.21
   125.9 1359.91   127.1 1360.54   135.8 1365.73   139.6 1366.65     159 1368.13
   211.9  1369.4   238.4 1369.65   248.3 1370.46   254.9 1371.92   258.2 1373.08
   264.8 1377.35   274.8 1384.71   284.7 1395.41     288 1398.56   296.7 1404.78
#Mann= 8 ,-1 , 0
       0      .1       0    79.5    .016       0    96.6      .1       0
   107.4    .045       0   127.1      .1       0   211.9     .04       0
   264.8      .1       0   296.7     .04       0
#Block Obstruct= 1 ,-1
   212.8  245.14 1390.14
Bank Sta=107.4,127.1
XS Rating Curve= 0 ,0
Exp/Cntr(USF)=0,0
Exp/Cntr=0.3,0.1

Type RM Length L Ch R = 1 ,1478    ,116.3,134.7,141.6
XS GIS Cut Line= 4
 2001195.8664862257543.8004658292001192.80735357257754.880617257
2001252.46043985257881.8346213762001277.81788685257969.817291181
#Sta/Elev= 30
       0 1397.19     8.4 1397.12    28.1 1395.65    47.8  1393.6      67 1389.05
    90.3 1380.12   100.3 1375.38   103.6 1373.52   116.4  1363.1   120.3  1361.4
   126.1 1360.48   142.9 1360.17   175.8  1360.5   255.4 1359.77     277 1357.85
   291.7 1357.24   299.8 1357.94   306.2 1362.19   309.8 1363.04   346.1 1365.03
   380.1 1366.32   388.1 1367.62   390.8 1368.38   394.2 1370.28   397.6 1372.94
   407.8 1381.49   417.2 1390.79   421.5 1394.21   435.1  1403.2   442.9 1407.73
#Mann= 7 ,-1 , 0
       0      .1       0   120.3    .016       0   142.9     .05       0
     277    .045       0   299.8      .1       0   346.1     .04       0
   388.1      .1       0
#XS Ineff= 2 , 0
          253.52 1368.49
Permanent Ineff=
       F       F
Bank Sta=277,299.8
XS Rating Curve= 0 ,0
Exp/Cntr(USF)=0,0
Exp/Cntr=0.5,0.3

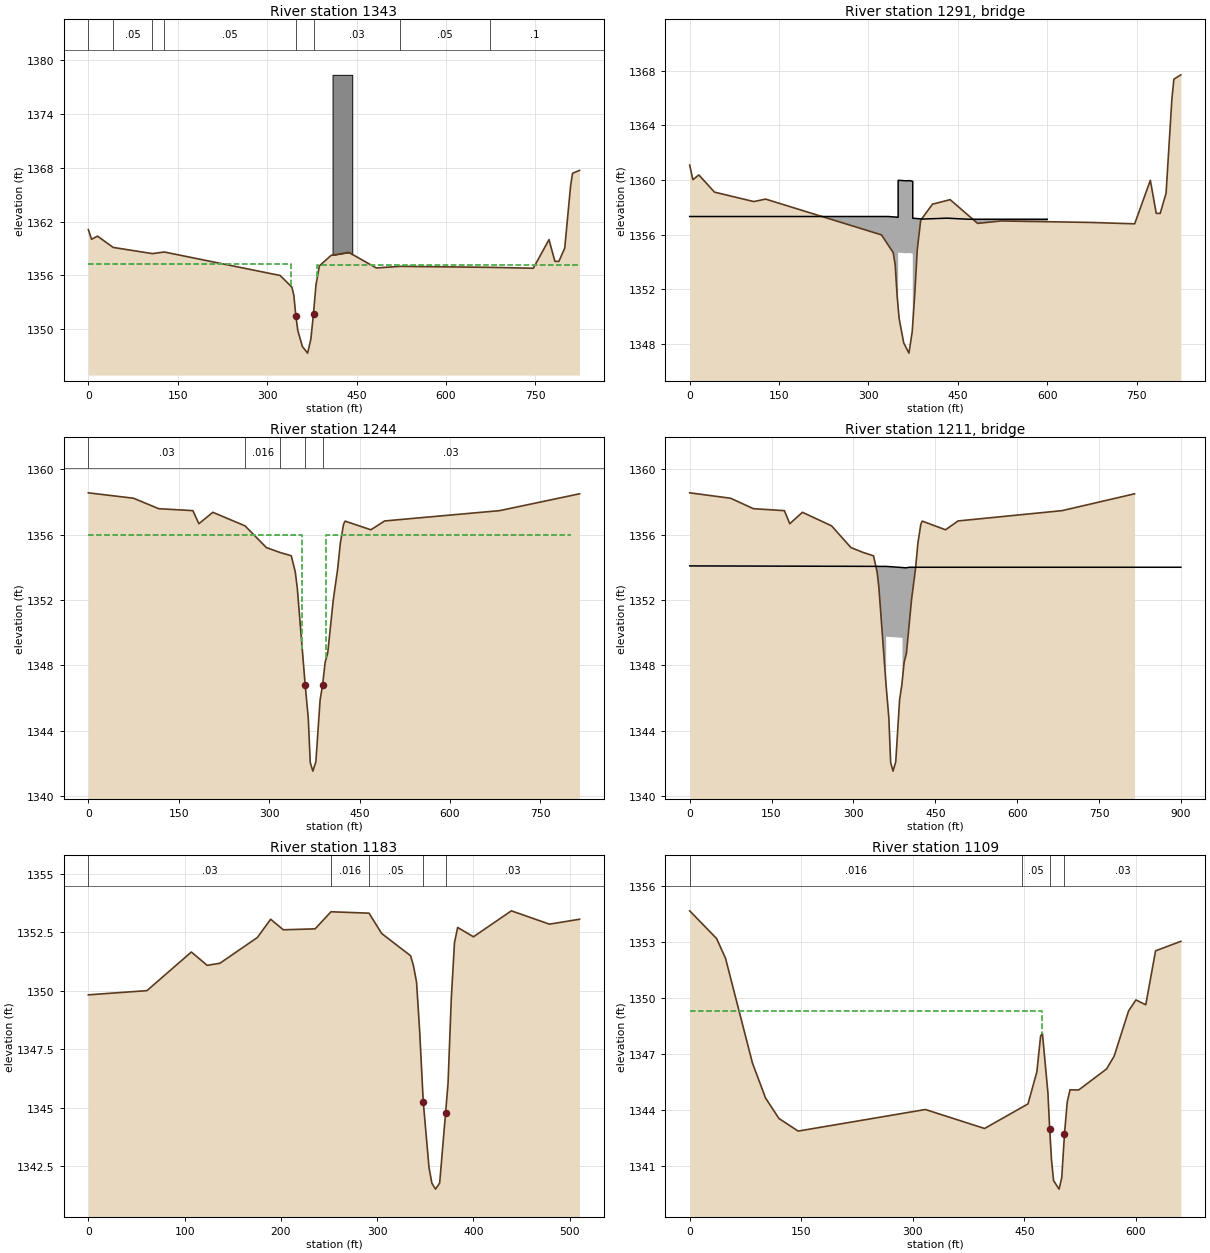
Type RM Length L Ch R = 1 ,1343    ,105,99.4,100.8
BEGIN DESCRIPTION:
Channel burned based on survey: 54089BRB032BU
END DESCRIPTION:
XS GIS Cut Line= 3
2001141.99403623257523.8448435722001113.10222807 257829.75810651
2001068.91475675258344.712099124
#Sta/Elev= 30
       0  1361.1     5.4 1360.03    15.3 1360.38    41.7 1359.12   107.6 1358.43
   127.4 1358.61   321.8 1355.99   341.5 1354.69   344.8 1353.78   348.1  1351.5
   351.4 1349.87  359.17 1348.07   367.91347.332  373.34  1348.9   377.8 1351.75
   381.9 1354.93   387.6 1357.06   407.4 1358.24     437 1358.57   483.1 1356.83
   522.7 1357.01   674.1  1356.9   746.6  1356.8   772.9 1359.99   782.8 1357.57
   789.4 1357.56   799.3 1359.04   809.1 1365.97   812.4 1367.39   824.1 1367.71
#Mann= 8 ,-1 , 0
       0      .1       0    41.7     .05       0   107.6    .016       0
   127.4     .05       0   348.1    .045       0   377.8     .03       0
   522.7     .05       0   674.1      .1       0
#XS Ineff= 2 , 0
          339.75 1357.32  384.25         1357.19
Permanent Ineff=
       F       F
#Block Obstruct= 1 ,-1
  409.72  442.74 1378.37
Bank Sta=348.1,377.8
XS Rating Curve= 0 ,0
Exp/Cntr(USF)=0,0
Exp/Cntr=0.5,0.3

Type RM Length L Ch R = 3 ,1291    ,,,
BEGIN DESCRIPTION:
State Route 20
Bridge Survey Number: 54089BRB030
Included a railing height of 2.7 ft based on survey report
END DESCRIPTION:
Bridge Culvert--1,0,-1,-1, 0
Deck Dist Width WeirC Skew NumUp NumDn MinLoCord MaxHiCord MaxSubmerge Is_Ogee
10,65,2.6,0, 13, 14, , , 0.98, 0, 0,0,,
       0     333  349.75  349.75     354     361     370  374.25  374.25     392
     432     467     600
1357.3361357.336 1357.28 1359.98 1359.981359.9531359.958 1359.91 1357.211357.151
1357.2141357.1361357.136
                         1354.68 1354.68 1354.65 1354.66 1354.61
                        
       0     333  359.75  359.75     364     371     380  384.25  384.25     392
     432     467     600     900
1357.3361357.336 1357.28 1359.98 1359.981359.9531359.958 1359.91 1357.211357.151
1357.2141357.1361357.1361357.136
                         1354.68 1354.68 1354.65 1354.66 1354.61
                                
BR Coef=-1 , 1 , 0 ,, 0 ,,,0.8,0,1.2,0,
WSPro=,,,, 1 ,,,, 0 ,,,, 0 ,,,,-1 ,-1 ,-1 , 0 , 0 , 0 , 0 , 0
BR U #Sta/Elev= 30
       0  1361.1     5.4 1360.03    15.3 1360.38    41.7 1359.12   107.6 1358.43
   127.4 1358.61   321.8 1355.99   341.5 1354.69   344.8 1353.78   348.1  1351.5
   351.4 1349.87  359.17 1348.07   367.91347.332  373.34  1348.9   377.8 1351.75
   381.9 1354.93   387.6 1357.06   407.4 1358.24     437 1358.57   483.1 1356.83
   522.7 1357.01   674.1  1356.9   746.6  1356.8   772.9 1359.99   782.8 1357.57
   789.4 1357.56   799.3 1359.04   809.1 1365.97   812.4 1367.39   824.1 1367.71
BR U #Mann= 8
       0      .1    41.7     .05   107.6    .016   127.4     .05   348.1     .04
   377.8     .03   522.7     .05   674.1      .1
BR D #Sta/Elev= 30
       0 1358.55    74.9 1358.22   116.8 1357.58   173.5 1357.46   183.4 1356.66
   206.6 1357.36     260 1356.53   295.5  1355.2   318.2  1354.9   336.8  1354.7
   343.4 1353.71   346.7 1352.75  359.811346.802  364.97 1344.77  368.24 1342.06
   372.61341.528  377.58  1342.1   384.6 1345.88  388.711346.795     393 1348.19
   397.2 1348.74   406.4 1351.98   413.8 1353.91   418.2 1355.48   423.5 1356.62
   426.1 1356.82   468.8 1356.29   491.8 1356.83   682.4 1357.46   815.1 1358.49
BR D #Mann= 5
       0     .03     260    .016   318.2     .03  359.81     .04  388.71     .03
BC Design=,, 0 ,, 0 ,,,,,,
BC Use User HTab Curves=0
BC User HTab FreeFlow(D)= 0

Type RM Length L Ch R = 1 ,1244    ,61.8,61.2,57.5
BEGIN DESCRIPTION:
Channel burned from survey: 54089BRB022BU
END DESCRIPTION:
XS GIS Cut Line= 6
2001089.77991858257549.9424346132001042.48763443257805.334521733
 2001019.6216891257855.7700825692001011.40999109257932.943092166
2001031.35192008 257958.020096962001021.96052003258347.913910327
#Sta/Elev= 30
       0 1358.55    74.9 1358.22   116.8 1357.58   173.5 1357.46   183.4 1356.66
   206.6 1357.36     260 1356.53   295.5  1355.2   318.2  1354.9   336.8  1354.7
   343.4 1353.71   346.7 1352.75  359.811346.802  364.97 1344.77  368.24 1342.06
   372.61341.528  377.58  1342.1   384.6 1345.88  388.711346.795     393 1348.19
   397.2 1348.74   406.4 1351.98   413.8 1353.91   418.2 1355.48   423.5 1356.62
   426.1 1356.82   468.8 1356.29   491.8 1356.83   682.4 1357.46   815.1 1358.49
#Mann= 5 ,-1 , 0
       0     .03       0     260    .016       0   318.2     .03       0
  359.81    .045       0  388.71     .03       0
#XS Ineff= 2 ,-1
       0     355    1356     395   800.7    1356
Permanent Ineff=
       F       F
Bank Sta=359.81,388.71
XS Rating Curve= 0 ,0
Exp/Cntr(USF)=0,0
Exp/Cntr=0.5,0.3

Type RM Length L Ch R = 3 ,1211    ,,,
BEGIN DESCRIPTION:
CSX
Survey Bridge Number: 54089BRB020
END DESCRIPTION:
Bridge Culvert--1,0,-1,-1, 0
Deck Dist Width WeirC Skew NumUp NumDn MinLoCord MaxHiCord MaxSubmerge Is_Ogee
10,31,2.6,0, 8, 8, , , 0.98, 0, 0,0,,
       0     360     360     390     390     396     402     900
 1354.08 1354.05 1354.05 1353.98 1353.981353.9621353.9971353.997
                 1349.75 1349.68
       0     345     345     375     375     386     402     900
 1354.08 1354.06 1354.06 1353.99 1353.991353.9621353.9971353.997
                 1349.76 1349.69
BR Coef=-1 , 1 , 0 ,, 0 ,,,0.8,0,1.2,0,
WSPro=,,,, 1 ,,,, 0 ,,,, 0 ,,,,-1 ,-1 ,-1 , 0 , 0 , 0 , 0 , 0
BR U #Sta/Elev= 30
       0 1358.55    74.9 1358.22   116.8 1357.58   173.5 1357.46   183.4 1356.66
   206.6 1357.36     260 1356.53   295.5  1355.2   318.2  1354.9   336.8  1354.7
   343.4 1353.71   346.7 1352.75  359.811346.802  364.97 1344.77  368.24 1342.06
   372.61341.528  377.58  1342.1   384.6 1345.88  388.711346.795     393 1348.19
   397.2 1348.74   406.4 1351.98   413.8 1353.91   418.2 1355.48   423.5 1356.62
   426.1 1356.82   468.8 1356.29   491.8 1356.83   682.4 1357.46   815.1 1358.49
BR U #Mann= 5
       0     .03     260    .016   318.2     .03  359.81     .04  388.71     .03
BR D #Sta/Elev= 30
       0 1349.83    60.9 1350.01     107 1351.66   123.5 1351.09   136.7 1351.18
   175.6 1352.28   189.4 1353.06   202.6 1352.61   235.6 1352.65   252.1 1353.38
   291.6 1353.32   304.8 1352.45   334.8  1351.5   337.7 1351.09     341 1350.37
   344.2 1348.29  347.971345.253  353.92 1342.46  356.93 1341.78   360.71341.528
  365.02 1341.79  371.111344.764   373.7 1346.05   377.1 1349.68   380.4 1352.06
   383.7 1352.71   400.1 1352.31   439.5 1353.42   479.1 1352.85   510.3 1353.06
BR D #Mann= 5
       0     .03   252.1    .016   291.6     .05  347.97     .04  371.11     .03
BC Design=,, 0 ,, 0 ,,,,,,
BC Use User HTab Curves=0
BC User HTab FreeFlow(D)= 0

Type RM Length L Ch R = 1 ,1183    ,81.1,73.5,65.1
BEGIN DESCRIPTION:
Channel burned based on survey: 54089BRB022BU
END DESCRIPTION:
XS GIS Cut Line= 5
2000988.52337748257563.7569693372000959.63156932257869.670232276
2000952.47563239257974.1008223732000955.32419793258003.310840613
2000952.73157505258072.256899831
#Sta/Elev= 30
       0 1349.83    60.9 1350.01     107 1351.66   123.5 1351.09   136.7 1351.18
   175.6 1352.28   189.4 1353.06   202.6 1352.61   235.6 1352.65   252.1 1353.38
   291.6 1353.32   304.8 1352.45   334.8  1351.5   337.7 1351.09     341 1350.37
   344.2 1348.29  347.971345.253  353.92 1342.46  356.93 1341.78   360.71341.528
  365.02 1341.79  371.111344.764   373.7 1346.05   377.1 1349.68   380.4 1352.06
   383.7 1352.71   400.1 1352.31   439.5 1353.42   479.1 1352.85   510.3 1353.06
#Mann= 5 ,-1 , 0
       0     .03       0   252.1    .016       0   291.6     .05       0
  347.97    .045       0  371.11     .03       0
#XS Ineff= 2 , 0
        339.3333 1349.76380.6667         1349.76
Permanent Ineff=
       F       F
Bank Sta=347.97,371.11
XS Rating Curve= 0 ,0
Exp/Cntr(USF)=0,0
Exp/Cntr=0.5,0.3

Type RM Length L Ch R = 1 ,1109    ,148.9,144.5,137.8
XS GIS Cut Line= 6
2001023.96955367257504.5937582782000908.50099549257680.882832497
2000881.41519735257817.4254053682000873.07239961257920.107401846
2000913.14021118257997.931420457 2000902.4464872258117.515445987
#Sta/Elev= 30
       0 1354.69    36.2  1353.2    48.2 1352.14    84.4 1346.51     102 1344.63
     120 1343.53   145.9 1342.85     317 1344.01   396.6 1342.99     455 1344.31
   466.9 1346.03     472 1347.96   474.4  1348.1   481.8 1344.91   484.2 1342.95
   486.6 1341.31   489.4 1340.19   496.8 1339.73   500.4 1340.35   504.1 1342.71
   507.8 1344.42   511.5 1345.07   523.2 1345.06   560.7 1346.19   570.9 1346.88
   590.3 1349.31   600.2  1349.9   613.4 1349.64   626.6 1352.54   660.6 1353.05
#Mann= 4 ,-1 , 0
       0    .016       0   446.5     .05       0   484.2    .045       0
   504.1     .03       0
#XS Ineff= 2 , 0
           473.8 1349.32
Permanent Ineff=
       F       F
#Block Obstruct= 2 , 0
                          701.89         1373.89
Bank Sta=484.2,504.1
XS Rating Curve= 0 ,0
Exp/Cntr(USF)=0,0
Exp/Cntr=0.3,0.1

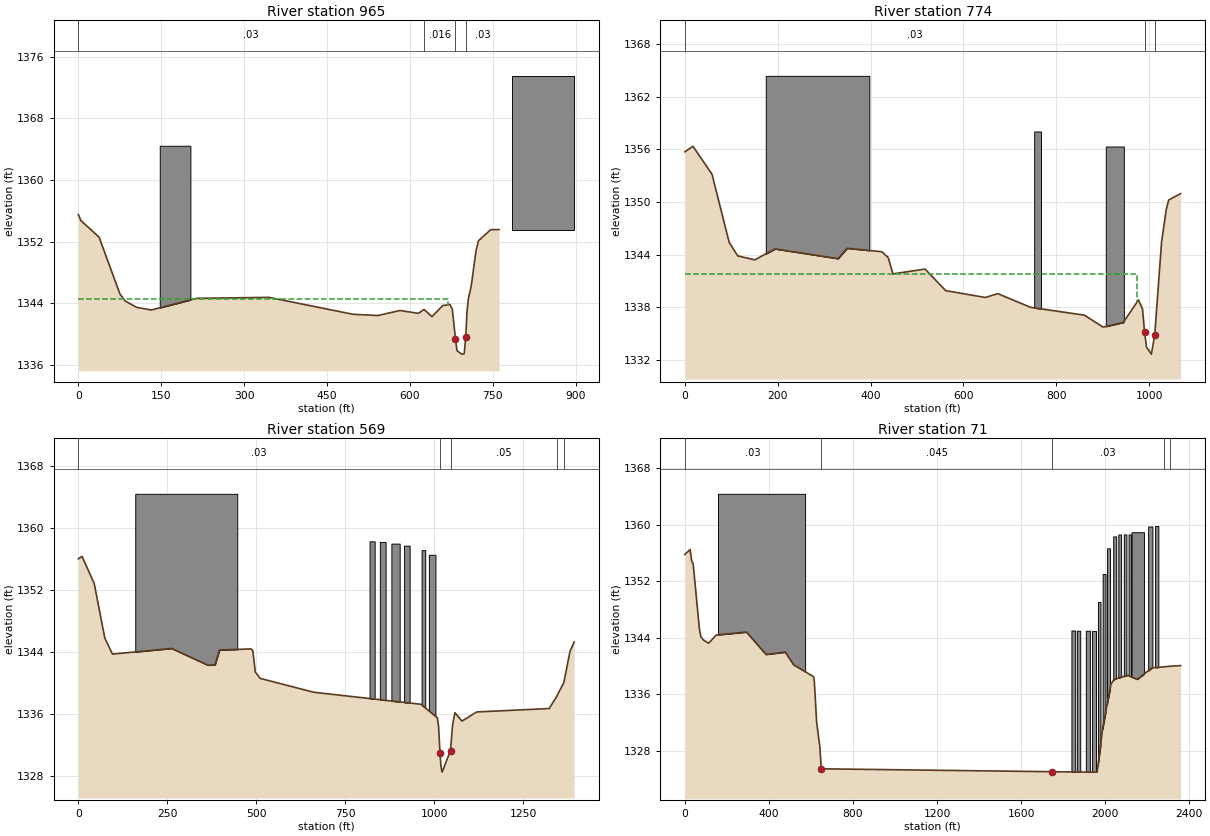
Type RM Length L Ch R = 1 ,965     ,190.2,190.3,191.6
XS GIS Cut Line= 6
2001030.31076527257482.4023772092000889.16641021257627.981900301
2000854.69389207257682.5678455942000785.71473041258048.669655636
2000864.13565944258115.0007914452000876.20417423258129.416484434
#Sta/Elev= 30
       0 1355.52     4.6 1354.74    37.6 1352.58    75.3 1345.21    84.7 1344.31
     105 1343.49   131.9 1343.13   214.1 1344.65   345.2 1344.77   496.9 1342.58
     542 1342.42   582.1 1343.07   615.4  1342.7   625.5 1343.21   639.9 1342.28
   659.5 1343.71   672.4 1343.85   676.7 1343.24   682.4 1339.41   685.3 1337.85
   693.9 1337.41   698.2 1337.46     701 1339.68   703.3 1342.91   705.7 1344.56
   711.1 1346.31   719.6 1350.83     724 1352.11     746 1353.55   761.4 1353.57
#Mann= 4 ,-1 , 0
       0     .03       0   625.5    .016       0   682.4    .045       0
     701     .03       0
#XS Ineff= 2 , 0
          668.17  1344.5
Permanent Ineff=
       F       F
#Block Obstruct= 2 ,-1
  147.32  202.77 1364.44  785.11  897.19 1373.51
Bank Sta=682.4,701
XS Rating Curve= 0 ,0
Exp/Cntr(USF)=0,0
Exp/Cntr=0.3,0.1

Type RM Length L Ch R = 1 ,774     ,178.3,205.1,215.2
XS GIS Cut Line= 6
2001052.86007459257436.0867012472000768.52134446257713.735108315
2000626.40707722258158.7562771112000688.23746772258211.049122583
 2000769.6363983258281.2975147322000783.67829438258285.765153454
#Sta/Elev= 30
       0 1355.73    17.6 1356.36    58.6 1353.18    95.6  1345.4   113.9 1343.87
   150.6 1343.41   194.4 1344.66     330 1343.55   349.4 1344.73   424.2 1344.34
     438 1343.67   448.3 1341.81   517.4 1342.36   561.9  1339.9   647.4 1339.12
     674 1339.56   744.5    1338   860.8  1337.1   900.8 1335.74   944.3 1336.27
   977.1 1338.84   985.8  1337.8   990.1 1335.18   994.5 1333.45  1004.8 1332.66
    1012 1334.81  1026.8 1345.45  1036.9 1349.16  1042.1 1350.24  1067.8 1350.97
#Mann= 3 , 0 , 0
       0     .03       0   990.1    .045       0    1012     .03       0
#XS Ineff= 2 , 0
          974.87 1341.83
Permanent Ineff=
       F       F
#Block Obstruct= 3 ,-1
  174.34  397.41  1364.4   752.4  767.16 1358.05  906.57  945.55 1356.34
Bank Sta=990.1,1012
XS Rating Curve= 0 ,0
Exp/Cntr(USF)=0,0
Exp/Cntr=0.3,0.1

Type RM Length L Ch R = 1 ,569     ,604.9,498.4,411
XS GIS Cut Line= 5
2001051.53745803257414.9842420462000708.23479621257700.503287516
2000558.67720097258206.9596895992000558.67720097258310.630295395
2000704.83575996258589.351268353
#Sta/Elev= 30
       0 1356.02    10.4 1356.34    44.6 1352.85    74.4 1345.81    95.8 1343.74
   262.2 1344.47   364.1 1342.31   383.9 1342.36   396.7 1344.27   485.3 1344.41
   490.3 1344.16   497.2 1341.44   510.8 1340.61   661.4 1338.82   962.4 1337.27
  1008.8 1335.53  1012.1 1334.42  1016.1    1331  1018.7 1329.28    1022 1328.52
  1045.6 1331.29  1051.5 1334.63    1058 1336.19  1077.7  1335.1  1119.1 1336.28
  1322.8 1336.72  1343.5 1338.24  1364.1 1340.09  1381.4  1344.1    1393 1345.31
#Mann= 5 ,-1 , 0
       0     .03       0  1016.1    .045       0  1045.6     .05       0
  1343.5    .016       0  1364.1     .05       0
#Block Obstruct= 7 ,-1
  159.88  446.52 1364.41  818.13  832.55 1358.29  846.97  863.29 1358.21
  879.49  902.82 1357.99  915.17  930.81 1357.73  964.36  974.59 1357.15
  984.79  1003.3 1356.55
Bank Sta=1016.1,1045.6
XS Rating Curve= 0 ,0
Exp/Cntr(USF)=0,0
Exp/Cntr=0.3,0.1

Type RM Length L Ch R = 1 ,71      ,71,71,71
XS GIS Cut Line= 5
2001072.70799866257361.4808935782000271.20685691257764.329634982
2000076.07699779258106.3314310692000063.48797462258309.853972299
 2000583.8342656259000.152076059
#Sta/Elev= 30
       0 1355.77    25.3 1356.47    32.7 1354.86      40 1354.41    69.4 1345.22
    76.7 1344.09    88.7 1343.65   113.5  1343.2   150.2 1344.37   293.4 1344.78
   386.2 1341.61   478.1 1341.94   517.4 1340.15   612.8 1338.46   616.5 1337.72
   627.5 1331.96   642.2 1328.61   649.6 1325.41  1745.6    1325  1934.6 1324.94
  1961.9 1324.94  1989.1 1331.29  2027.3 1337.36  2042.4  1338.1  2107.2 1338.65
  2152.6 1338.09  2223.5 1339.72    2279 1339.85  2308.5 1339.94  2359.2 1340.03
#Mann= 5 ,-1 , 0
       0     .03       0   649.6    .045       0  1745.6     .03       0
    2279    .016       0  2308.5     .05       0
#Block Obstruct= 15 ,-1
  157.86  572.51 1364.36 1839.64 1857.47    1345 1865.46 1881.51 1344.97
 1907.91 1927.46 1344.97 1938.13 1957.34 1344.94 1965.65 1977.88 1349.03
 1988.21 2001.89 1353.01 2009.04 2023.48 1356.64 2038.47 2052.68 1358.33
 2062.69 2076.11  1358.6 2088.92 2101.25 1358.61 2111.51 2122.95 1358.61
 2125.68 2184.63 1358.92 2204.61 2224.91 1359.73 2237.73 2253.26 1359.81
Bank Sta=649.6,1745.6
XS Rating Curve= 0 ,0
Exp/Cntr(USF)=0,0
Exp/Cntr=0.3,0.1
LCMann Table=0

Chan Stop Cuts=-1
Use User Specified Reach Order=0
Composite Channel Slope=5